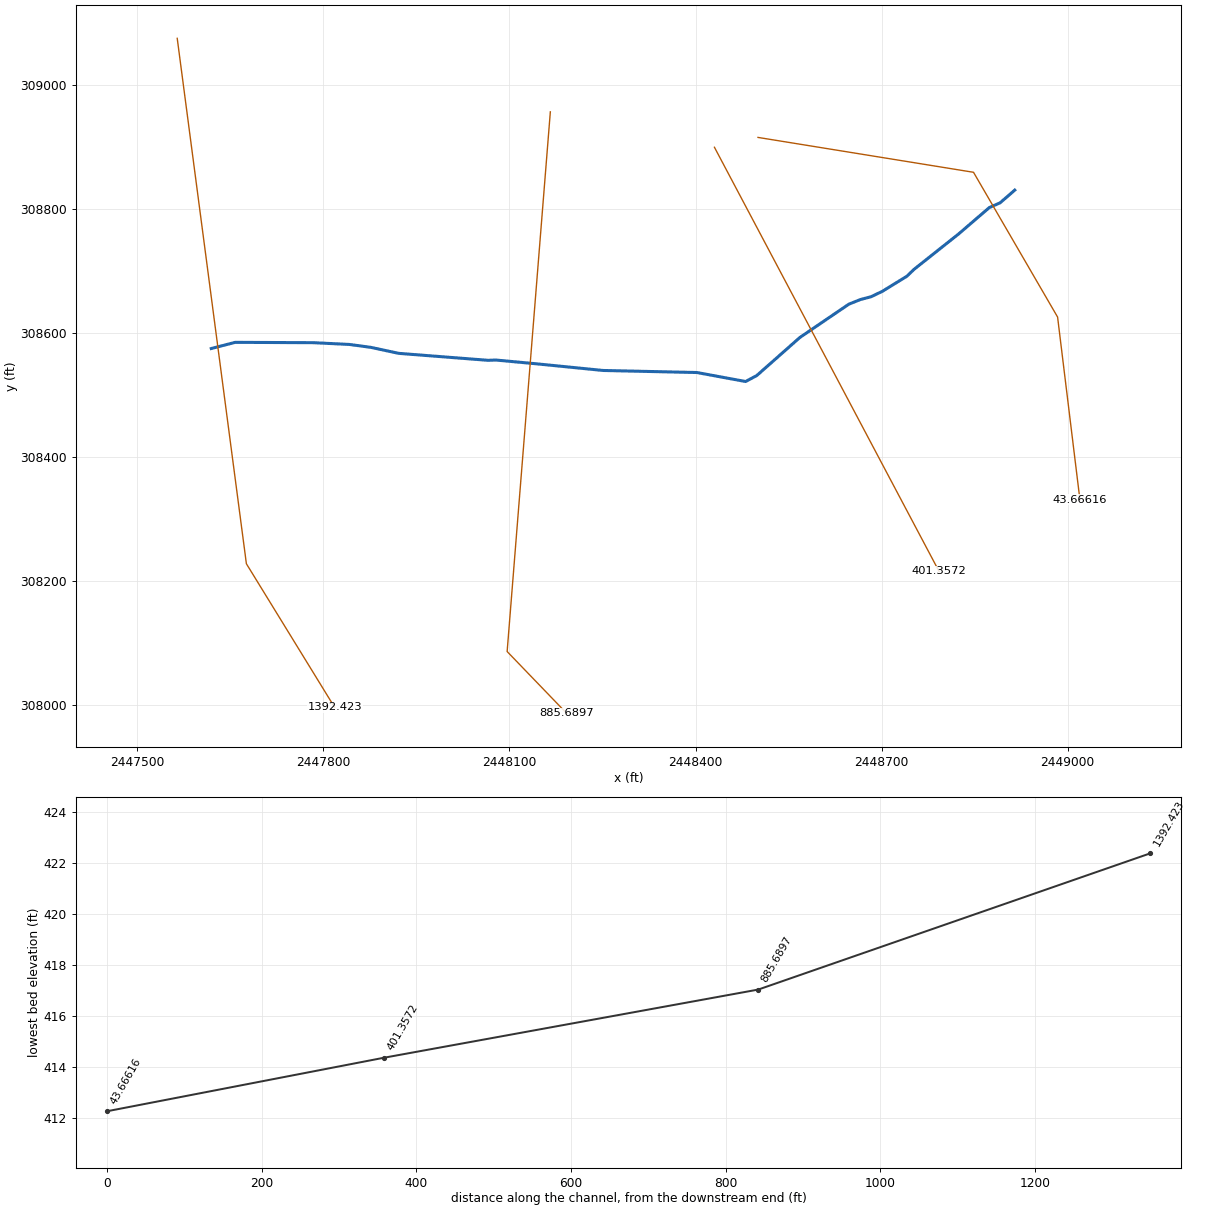
--- TribElksRun.prj (project) ---

Proj Title=TribElksRun
Current Plan=p01
Default Exp/Contr=0.3,0.1
English Units
Geom File=g01
Flow File=f01
Plan File=p01
Y Axis Title=Elevation
X Axis Title(PF)=Main Channel Distance
X Axis Title(XS)=Station
BEGIN DESCRIPTION:
END DESCRIPTION:
DSS Export Rating Curves= 0
DSS Export Rating Curve Sorted= 0
DSS Export Volume Flow Curves= 0
DXF OffsetX= 0
DXF OffsetY= 0
DXF ScaleX= 1
DXF ScaleY= 10

--- TribElksRun.p01 (plan) ---

Plan Title=Plan 01
Program Version=4.10
Short Identifier=Plan 01
Geom File=g01
Flow File=f01
Subcritical Flow
K Sum by GR= 0
Std Step Tol= 0.01
Critical Tol= 0.01
Num of Std Step Trials= 20
Max Error Tol= 0.3
Flow Tol Ratio= 0.001
Split Flow NTrial= 30
Split Flow Tol= 0.02
Split Flow Ratio= 0.02
Log Output Level= 0
Friction Slope Method= 1
Unsteady Friction Slope Method= 2
Unsteady Bridges Friction Slope Method= 1
Parabolic Critical Depth
Global Vel Dist= 0 , 0 , 0
Global Log Level= 0
CheckData=True
Encroach Param=-1 ,0,0, 0
Computation Interval=1HOUR
Output Interval=1HOUR
Run HTab= 0
Run UNet= 0
Run PostProcess= 0
Run WQNet= 0
UNET Theta= 1
UNET Theta Warmup= 1
UNET ZTol= 0.02
UNET ZSATol= 0.05
UNET MxIter= 20
UNET MaxInSteps= 0
UNET DtIC= 0
UNET DtMin= 0
UNET MaxCRTS= 20
UNET WFStab= 2
UNET SFStab= 1
UNET WFX= 1
UNET SFX= 1
UNET DSS MLevel= 4
UNET DZMax Abort= 100
UNET Convert EG Bridges= 0
UNET Use Existing IB Tables=-1
UNET Froude Reduction=False
UNET Froude Limit= 1
UNET Froude Power= 10
UNET Time Slicing=0,0, 5
UNET Junction Losses=0
Instantaneous Interval=1HOUR
Write IC File= 0
Write IC File at Sim End=0
Echo Input=False
Echo Parameters=False
Echo Output=False
Write Detailed= 0
WQ AD Non Conservative
WQ ULTIMATE=-1
WQ Max Comp Step=1HOUR
WQ Output Interval=15MIN
WQ Output Selected Increments= 0
WQ Output face flow=0
WQ Output face velocity=0
WQ Output face area=0
WQ Output face dispersion=0
WQ Output cell volume=0
WQ Output cell surface area=0
WQ Output cell continuity=0
WQ Output cumulative cell continuity=0
WQ Output face conc=0
WQ Output face dconc_dx=0
WQ Output face courant=0
WQ Output face peclet=0
WQ Output face adv mass=0
WQ Output face disp mass=0
WQ Output cell mass=0
WQ Output cell source sink temp=0
WQ Output cell source sink nsm=0
WQ Output MaxMinRange=-1
WQ Daily Max Min Mean=-1
WQ Daily Range=0
WQ Daily Time=0
WQ Create Restart=0
WQ Fixed Restart=0
WQ System Summary=0
WQ Use Fixed Temperature=0
Sorting and Armoring Iterations= 10
XS Update Threshold= 0.02
Hydraulics Update Threshold= 0.02
Energy Slope Method= 1
Volume Change Method= 0
XS Weighting Method= 0
Number of US Weighted Cross Sections= 1
Number of DS Weighted Cross Sections= 1
Upstream XS Weight=0.25
Main XS Weight=0.5
Downstream XS Weight=0.25
Number of DS XS's Weighted with US Boundary= 1
Upstream Boundary Weight= 1
Weight of XSs Associated with US Boundary= 0
Number of US XS's Weighted with DS Boundary= 1
Downstream Boundary Weight= 0.5
Weight of XSs Associated with DS Boundary= 0.5
Sediment Output Level= 4
Mass or Volume Output= 0
Output Increment Type= 1
Profile and TS Output Increment= 10
XS Output Flag= 0
XS Output Increment= 10
Disregard all LS=0
Disregard all Conn=0
Disregard all Breaches=0
Disregard all Pumps=0

--- TribElksRun.f01 (steady flow) ---

Flow Title=TribElksRun
Program Version=4.10
Number of Profiles= 1
Profile Names=PF 1
River Rch & RM=UNT1ElksRun,Reach1          ,1392.423
     830
Boundary for River Rch & Prof#=UNT1ElksRun,Reach1          , 1
Up Type= 0
Dn Type= 3
Dn Slope=0.00623
DSS Import GetInterval= 0
DSS Import GetPeak= 0
DSS Import FillOption= 0

--- TribElksRun.g01 (geometry) ---

Geom Title=TribElkRun
Program Version=4.10

River Reach=UNT1ElksRun     ,Reach1
Reach XY= 30
2447619.11025836308574.3539036072447657.73879002308584.336495191
2447784.19424577308583.7492260192447841.78402561308580.939192265
2447876.19931111308576.2925480162447921.33832844308566.570454597
2448065.56573027308555.3290072682448077.93545619308555.806368515
2448141.52030277308549.903493181 2448250.8954121308538.966179103
2448402.20318036308535.6686135232448462.27261403308524.557743356
2448480.74075294308521.1722514332448498.73120253308530.807730854
 2448568.2277827308592.1645635222448647.23385827308645.890177846
2448665.74366377308653.2917378542448683.10616186308657.890810013
2448701.16157193308666.5715669392448709.07822278308671.432777688
2448711.71732511308673.0528531822448730.18940103308684.395678267
2448740.74515419308690.8769645242448752.14112878308701.888097361
2448824.42543302308759.279714853 2448873.7311087308801.640850604
2448891.09229444 308809.279942932448902.89804511308819.522704601
2448905.25893277308821.571585014 2448914.7034677308829.765794352

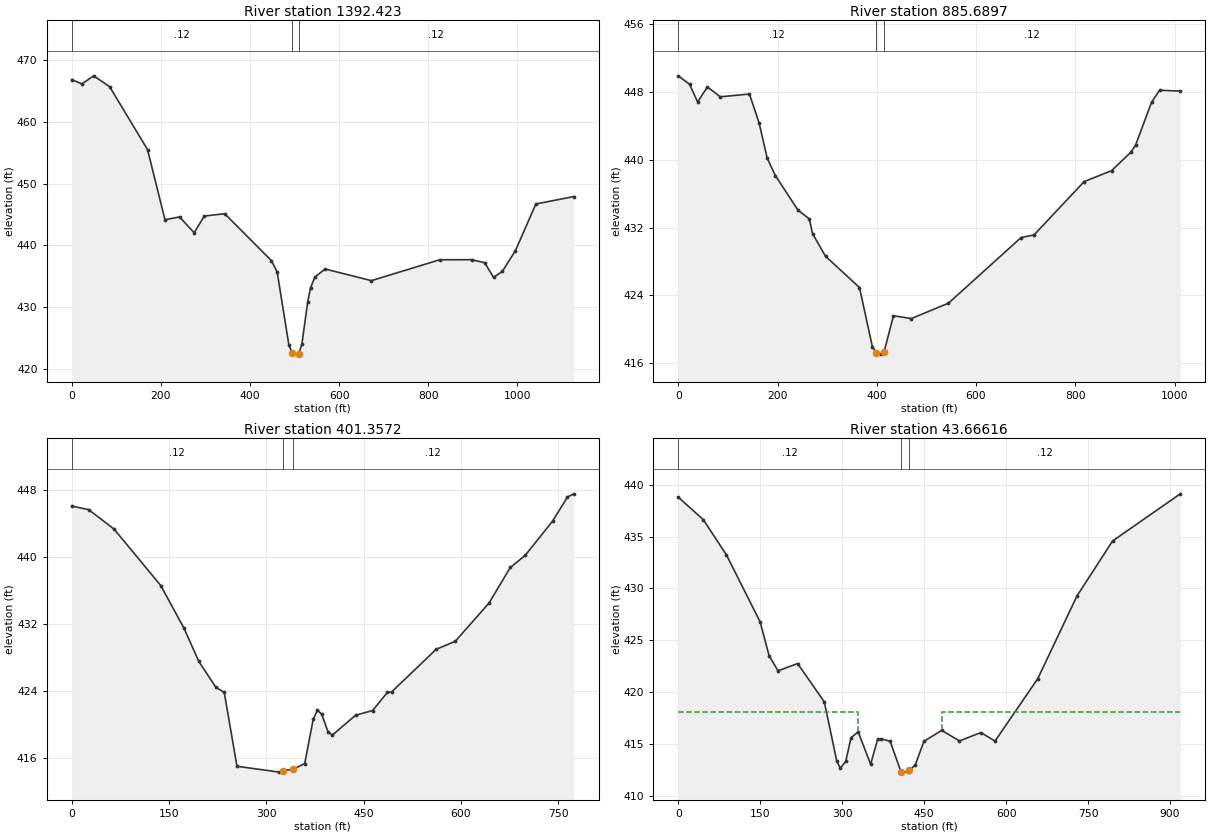
Type RM Length L Ch R = 1 ,1392.423,512.94,506.73,500.11
Node Name=967
XS GIS Cut Line= 4
2447564.20748103  309074.53597412447629.90387194 308575.51466243
2447675.74531569308227.3099782762447818.13938786 307995.59357819
#Sta/Elev= 30
       0  466.89   22.88  466.19   49.03   467.5   84.98  465.74  169.95  455.55
  209.17  444.17  241.86  444.63  274.54  442.07  297.42  444.77  343.18  445.15
  447.77  437.56  460.84  435.71  486.99  423.94  494.24  422.63  506.58  422.39
  509.12  422.42  516.34  424.02  529.34  430.83  535.85  433.17   545.6  434.89
  568.37  436.19  672.43   434.3  825.27  437.68  897.13   437.7  926.63   437.2
  946.29  434.83  965.95  435.79  995.44  439.16 1041.31  446.73 1126.51  447.93
#Mann= 3 , 0 , 0
       0     .12       0  494.24    .045       0  509.12     .12       0
Bank Sta=494.24,509.12
XS Rating Curve= 0 ,0
Exp/Cntr=0.3,0.1

Type RM Length L Ch R = 1 ,885.6897,466.33,484.33,501.18
Node Name=968
XS GIS Cut Line= 4
2448165.85522786308956.0240720212448126.05215786308458.788846016
2448096.19329369308085.7797495132448192.27118553307986.044712767
#Sta/Elev= 30
       0  449.93   22.82  448.93   39.12  446.84   58.69  448.62   84.77  447.45
  143.45  447.78  163.01  444.34  179.32  440.19  195.62  438.15  241.26  434.06
  264.08  433.02   270.6  431.28  296.69  428.61  365.15  424.91  391.24  417.89
  399.41  417.18  407.54  417.04  414.41  417.24  433.62  421.58  469.48  421.24
  544.38  423.06  690.81  430.82  716.84  431.13  817.71  437.43  873.03  438.72
  911.67  440.89  921.34  441.73  953.54   446.8  969.65  448.23 1011.51  448.12
#Mann= 3 , 0 , 0
       0     .12       0  399.41    .045       0  414.41     .12       0
Bank Sta=399.41,414.41
XS Rating Curve= 0 ,0
Exp/Cntr=0.3,0.1

Type RM Length L Ch R = 1 ,401.3572,356.17,357.69,358.53
Node Name=969
XS GIS Cut Line= 3
 2448430.4442656308898.9021390232448615.35990627308549.768322855
2448792.74078511 308214.86085619
#Sta/Elev= 30
       0  446.08   26.12  445.65    65.3  443.33  137.14  436.61  173.05  431.51
  195.91  427.55  222.03  424.49  235.09  423.86  254.68  415.06  319.98  414.36
   325.6  414.55  340.69  414.68  359.16  415.38  372.22  420.66  378.75  421.75
  385.28  421.27  395.08  419.16  401.61  418.77  437.55  421.14  463.69   421.7
  486.56  423.86  493.09  423.92   561.7     429  591.11  429.95  643.38  434.53
  676.05  438.76  698.92  440.19  741.39   444.3  764.26  447.17  774.06  447.54
#Mann= 3 , 0 , 0
       0     .12       0   325.6    .045       0  340.69     .12       0
Bank Sta=325.6,340.69
XS Rating Curve= 0 ,0
Exp/Cntr=0.3,0.1

Type RM Length L Ch R = 1 ,43.66616,41.67,43.67,51.41
Node Name=970
XS GIS Cut Line= 5
2448500.69150044308914.7774353472448848.23017544 308858.53771843
2448875.97191785 308810.765832352448983.78502244308625.111019939
2449019.78855936308330.576175943
#Sta/Elev= 30
       0   438.8   45.64  436.64   88.01  433.25  149.95  426.75  166.25   423.5
  182.55  422.04  218.41  422.74   267.3  419.04  290.12  413.32  296.64  412.64
  306.42  413.29   316.2  415.58  329.24  416.15  352.06  413.02  365.06  415.46
  371.56  415.47   387.8  415.24  407.38  412.32  420.05  412.26  422.24  412.45
  433.33  412.91  449.59  415.23  482.12  416.29  514.65  415.27  553.68  416.08
   579.7  415.26  657.86  421.28   729.6  429.26  794.81  434.57  918.72  439.12
#Mann= 3 , 0 , 0
       0     .12       0  407.38    .045       0  422.24     .12       0
#XS Ineff= 2 , 0
          329.58  418.03  482.25          418.06
Permanent Ineff=
       F       F
Bank Sta=407.38,422.24
XS Rating Curve= 0 ,0
Exp/Cntr=0.3,0.1

Chan Stop Cuts=-1
Use User Specified Reach Order=0
Composite Channel Slope=5